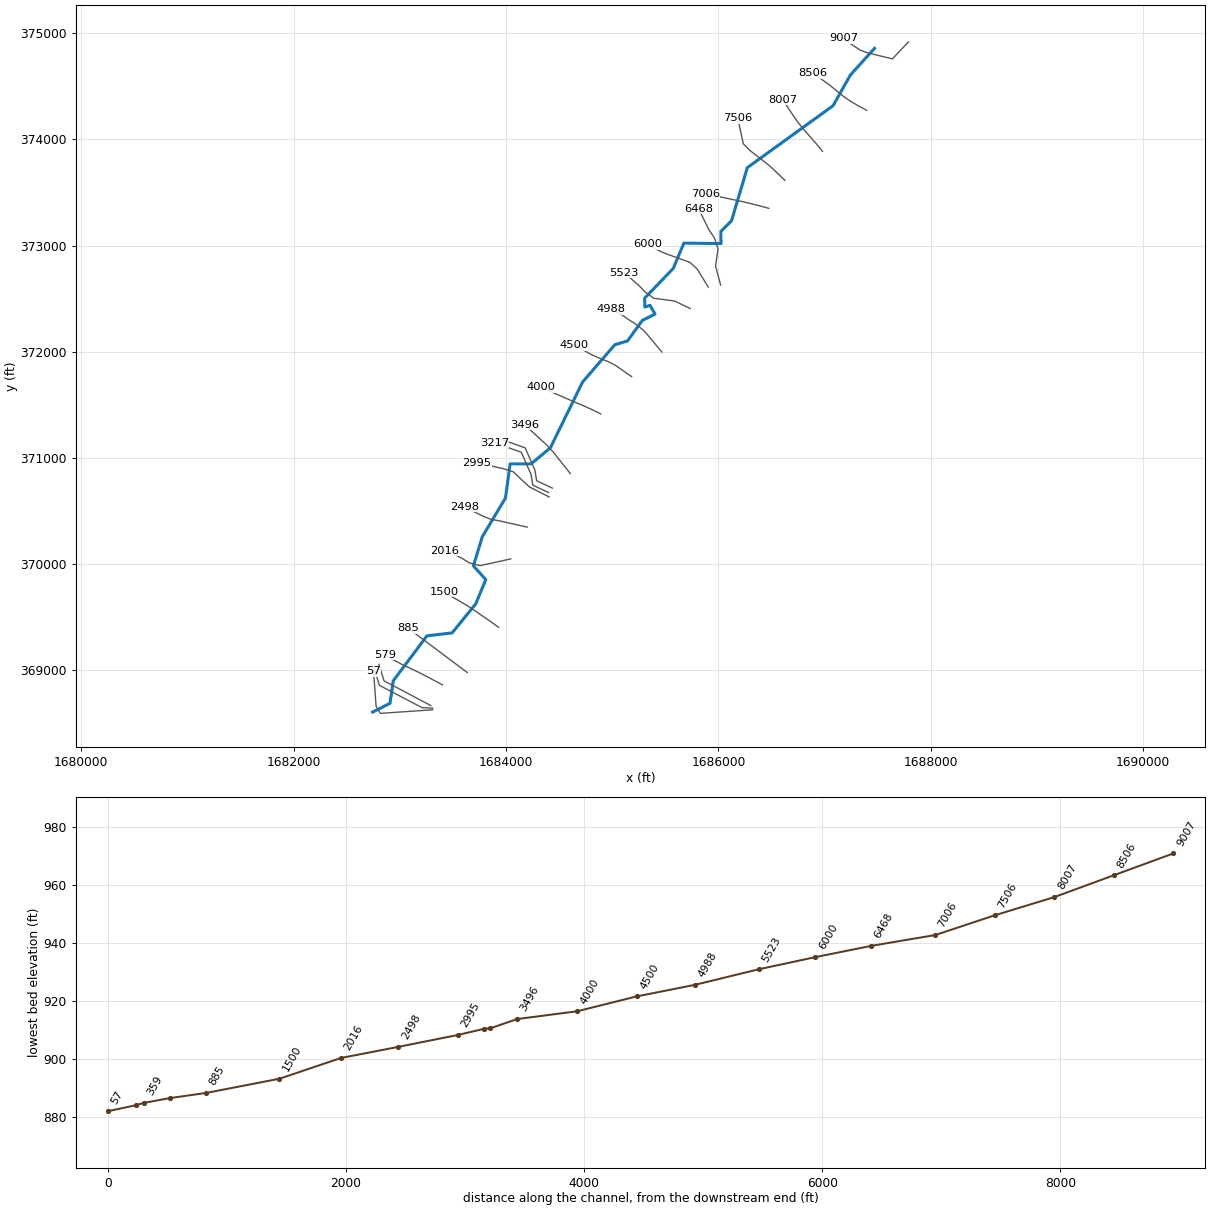
--- PCKNPWRN.prj (project) ---

Proj Title=PCKNPWRN
Current Plan=p01
Default Exp/Contr=0,0
English Units
Geom File=g01
Flow File=f01
Plan File=p01
BEGIN DESCRIPTION:
---------- MODELED AS PART OF WVEMD CTP PROGRAM, 2023----------
Stream Name: Pickenpaw Run
Flood Zone:  AFH
Wetzel County, WV
HEC-RAS Version: RAS 6.3
Vertical Datum: NAVD88
Projection: NAD 1983 StatePlane West Virginia S FIPS 4702 (US Feet)
Terrain: 1-meter West Virginia FEMA R3 South Central (collected 2018-2020)
Land Use: 2019 NLCD
Hydrologic Method:
WV 2010 Regional Regression Equations
Additional Model Notes:
None
END DESCRIPTION:
DSS Export Rating Curves= 0
DSS Export Rating Curve Sorted= 0
DSS Export Volume Flow Curves= 0
DXF OffsetX= 0
DXF OffsetY= 0
DXF ScaleX= 0
DXF ScaleY= 0

--- PCKNPWRN.p01 (plan) ---

Plan Title=Floodplain
Program Version=6.30
Short Identifier=Floodplain
Geom File=g01
Flow File=f01
Subcritical Flow
K Sum by GR= 0
Std Step Tol= 0.01
Critical Tol= 0.01
Num of Std Step Trials= 20
Max Error Tol= 0.3
Flow Tol Ratio= 0.001
Split Flow NTrial= 30
Split Flow Tol= 0.02
Split Flow Ratio= 0.02
Log Output Level= 0
Friction Slope Method= 1
Unsteady Friction Slope Method= 2
Unsteady Bridges Friction Slope Method= 1
Parabolic Critical Depth
Global Vel Dist= 0 , 0 , 0
Global Log Level= 0
CheckData=False
Encroach Param=-1 ,0,0, 0
Mapping Interval=1HOUR
Computation Time Step Use Courant=        0
Computation Time Step Use Time Series=    0
Computation Time Step Count To Double=0
Computation Time Step Max Doubling=0
Computation Time Step Max Halving=0
Computation Time Step Residence Courant=0
Run HTab= 0
Run UNet= 0
Run Sediment= 0
Run PostProcess= 0
Run WQNet= 0
Run RASMapper=-1
UNET Theta= 0
UNET Theta Warmup= 0
UNET ZTol= 0
UNET ZSATol= 0
UNET MxIter= 0
UNET Max Iter WO Improvement= 0
UNET MaxInSteps= 0
UNET DtIC= 0
UNET DtMin= 0
UNET MaxCRTS= 0
UNET WFStab= 0
UNET SFStab= 0
UNET WFX= 1
UNET SFX= 1
UNET Gravity=32.17405
UNET 1D Methodology=Finite Difference
UNET DSS MLevel= 1
UNET Pardiso=0
UNET DZMax Abort= 0
UNET Use Existing IB Tables= 0
UNET Froude Reduction=False
UNET Froude Limit= 0
UNET Froude Power= 0
UNET D1 Cores= 0
UNET WindReference=Eulerian
UNET WindDragFormulation=Hsu (1988)
UNET D2 Coriolis=0
UNET D2 Cores= 0
UNET D2 Theta= 1
UNET D2 Theta Warmup= 1
UNET D2 Z Tol= 0.01
UNET D2 Volume Tol= 0.01
UNET D2 Max Iterations= 20
UNET D2 Equation= 0
UNET D2 RampUpFraction=0.1
UNET D2 TimeSlices= 1
UNET D2 Turbulence Formulation=Non-Conservative (original)
UNET D2 Eddy Viscosity=0.3
UNET D2 Transverse Eddy Viscosity=0.1
UNET D2 Smagorinsky Mixing=0
UNET D2 BCVolumeCheck=0
UNET D2 Cores=0
UNET D2 SolverType=PARDISO (Direct)
UNET D2 Minimum Iterations= 3
UNET D2 Maximum Iterations= 30
UNET D2 Restart Number= 10
UNET D2 Relaxation Coeff=1.3
UNET D2 SOR Precondition Iterations= 10
UNET D2 ILUT Maximum Fill= 8
UNET D2 ILUT Tolerance=1E-08
UNET D2 Convergence Tolerance=0.00001
UNET D1D2 MaxIter= 0
UNET D1D2 ZTol=0.01
UNET D1D2 QTol=0.1
UNET D1D2 MinQTol=1
Write IC File= 0
Write IC File at Fixed DateTime=0
Write IC File at Sim End=0
Echo Input=False
Echo Parameters=False
Echo Output=False
Write Detailed= 0
HDF Write Warmup=0
HDF Write Time Slices=0
HDF Flush=0
HDF Compression= 1
HDF Chunk Size= 1
HDF Spatial Parts= 1
HDF Use Max Rows=0
HDF Fixed Rows= 1
Calibration Method= 0
Calibration Iterations= 20
Calibration Max Change=0.05
Calibration Tolerance=0.2
Calibration Maximum=1.5
Calibration Minimum=0.5
Calibration Optimization Method= 1
WQ AD Non Conservative
WQ ULTIMATE=-1
WQ Max Comp Step=1HOUR
WQ Output Interval=15MIN
WQ Output Selected Increments= 0
WQ Output face flow=0
WQ Output face velocity=0
WQ Output face area=0
WQ Output face dispersion=0
WQ Output cell volume=0
WQ Output cell surface area=0
WQ Output cell continuity=0
WQ Output cumulative cell continuity=0
WQ Output face conc=0
WQ Output face dconc_dx=0
WQ Output face courant=0
WQ Output face peclet=0
WQ Output face adv mass=0
WQ Output face disp mass=0
WQ Output cell mass=0
WQ Output cell source sink temp=0
WQ Output nsm pathways=0
WQ Output nsm derived pathways=0
WQ Create Restart=0
WQ Fixed Restart=0
WQ System Summary=0
WQ Write To DSS=0
Sorting and Armoring Iterations= 10
XS Update Threshold= 0.02
Bed Roughness Predictor= 0
Hydraulics Update Threshold= 0.02
Energy Slope Method= 1
Volume Change Method= 1
Sediment Retention Method= 0
Sediment TS Multiplier= 1
Warm Up Method= 0
XS Weighting Method= 0
Number of US Weighted Cross Sections= 1
Number of DS Weighted Cross Sections= 1
Upstream XS Weight=0
Main XS Weight=1
Downstream XS Weight=0
Number of DS XS's Weighted with US Boundary= 1
Upstream Boundary Weight= 1
Weight of XSs Associated with US Boundary= 0
Number of US XS's Weighted with DS Boundary= 1
Downstream Boundary Weight= 0.5
Weight of XSs Associated with DS Boundary= 0.5
Percentile Method= 0
Sediment Output Level= 3
Mass or Volume Output= 0
Output Increment Type= 1
Profile and TS Output Increment= 1
Transport Output Increment 1
XS Output Flag= 0
XS Output Increment= 10
Read HDF5 Sediment Hotstart= 0
Sediment Hotstart Type= 0
Write Gradation File= 0
Read Gradation Hotstart= 0
Write HDF5 File= 1
Write Binary Output= 1
Write DSS Sediment File= 0
DSS Sediment Output Type= 1
SV Curve= 0
Specific Gage Flag= 0
Subcell Erosion Methods= 0
Subcell Deposition Methods= 0
Advection Scheme= 1
Matrix Solver= 0
Implicit Weighting Factor= 1
Maximum Outer Loop Convergence Iterations= 5
Convergence Maximum Absolute= 0.001
Convergence RMSE= 0.0001
Grain Fractions Max Abs Error= 0.001
Max Subgrid Regions= 1
Max Subgrid Length Scale= 3.402823E+38
Initial Layer Thickness= 3.402823E+38
Min Layer Thickness= 3.402823E+38
Max Layer Thickness= 3.402823E+38
Number of Layers= 5

--- PCKNPWRN.f01 (steady flow) ---

Flow Title=Flow
Program Version=6.31
Number of Profiles= 1
Profile Names=F01pct
River Rch & RM=PCKNPWRN,Main,9007
     660
River Rch & RM=PCKNPWRN,Main,7006
     980
River Rch & RM=PCKNPWRN,Main,4500
    1090
Boundary for River Rch & Prof#=PCKNPWRN,Main            , 1
Up Type= 0
Dn Type= 3
Dn Slope=0.00877
DSS Import GetInterval= 0
DSS Import GetPeak= 0
DSS Import FillOption= 0

--- PCKNPWRN.g01 (geometry) ---

Geom Title=Geometry
Program Version=6.31

River Reach=PCKNPWRN        ,Main
Reach XY= 30
     1687470.153      374858.359     1687243.436      374608.366
     1687079.293      374317.563     1686271.878      373734.447
     1686123.454      373234.762     1686023.093      373134.402
     1686024.001      373019.532     1685674.554      373024.066
     1685574.496       372785.56     1685305.156       372505.64
     1685307.272      372421.905     1685355.941      372437.927
     1685403.098      372355.402     1685282.786      372295.549
     1685144.036       372102.99     1685023.724      372066.413
      1684720.83       371716.06     1684417.634      371096.668
     1684234.749      370944.617      1684038.26      370945.221
     1683994.731      370623.888     1683776.478      370259.629
     1683693.046      369984.545     1683809.125      369855.468
     1683714.811      369627.239     1683492.326      369353.667
     1683254.726      369325.554     1682937.927      368902.349
     1682907.396      368690.746     1682743.886      368607.633

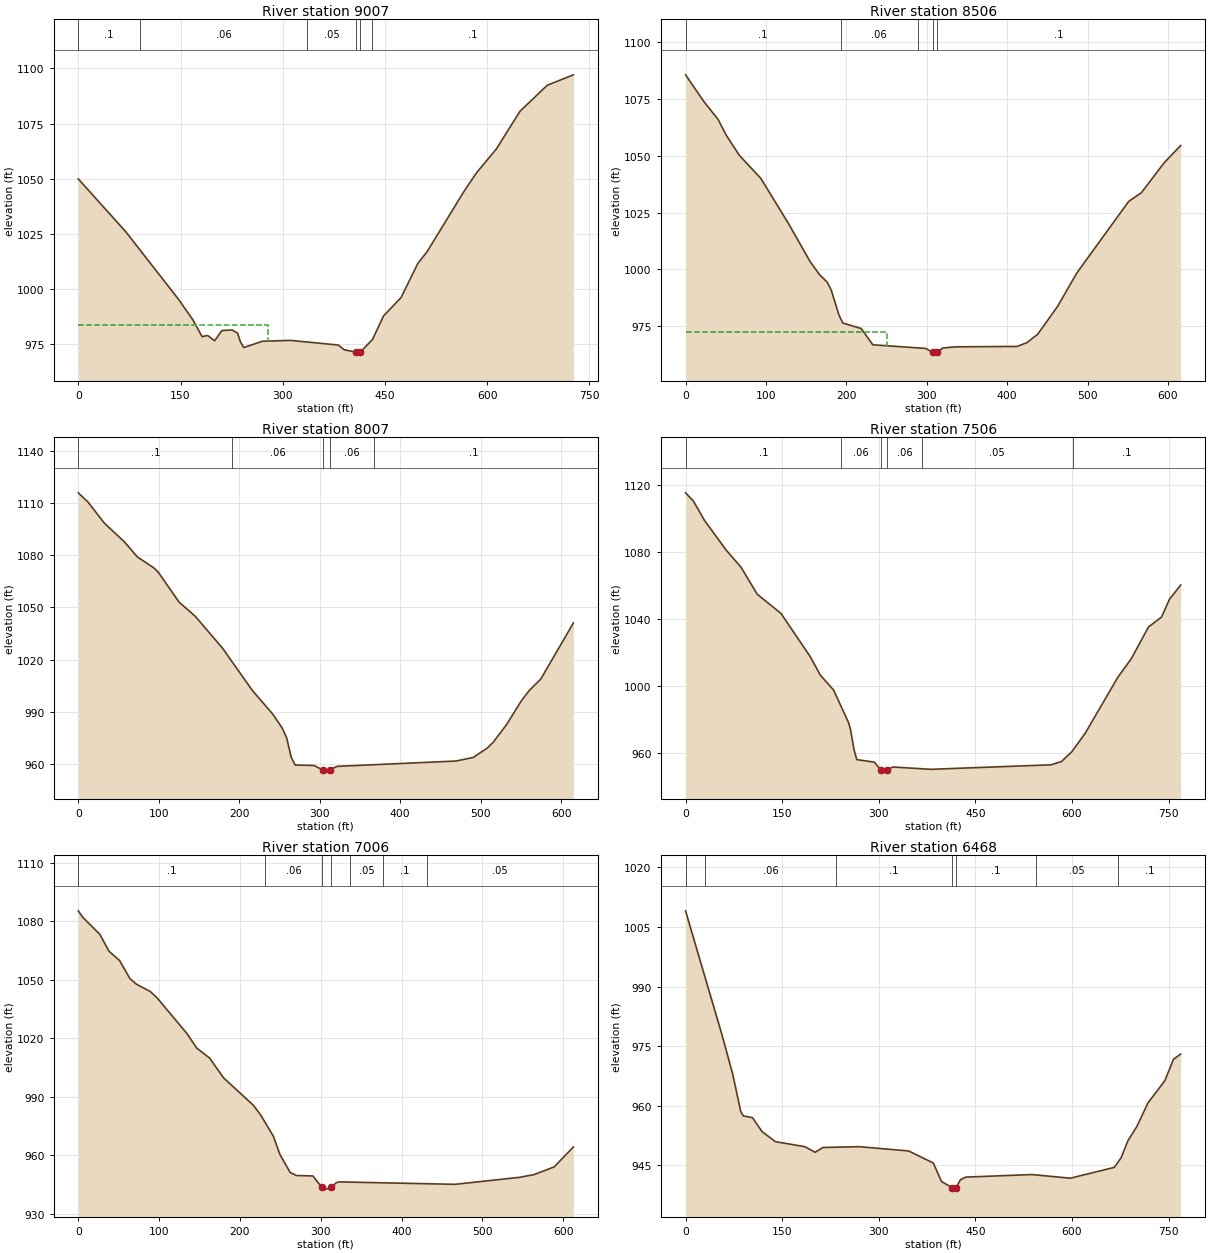
Type RM Length L Ch R = 1 ,9007    ,500.6,500.6,500.6
XS GIS Cut Line= 6
1687789.04954687374918.3253873811687638.02023083 374758.90978937
 1687403.7352965374815.546598837 1687332.6038771374842.365770921
1687256.28972526374892.6301060921687177.96015751374952.165420085
#Sta/Elev= 30
       0 1049.85    69.8 1025.82   146.8  995.31   167.8  986.03   181.7  978.26
   189.8  978.77     200  976.35   210.7  981.01   225.6  981.28   233.8  979.83
   237.9  975.92   242.9  973.29   270.1  976.15   311.6  976.54   381.7  974.42
     390  972.32   408.1  971.12   410.6  970.76  413.45 971.124   431.8     977
   447.9  987.64   473.6  995.99   498.4 1011.57   511.6  1016.7     566 1044.21
   584.8 1052.81   613.4 1063.42   648.1 1080.55   688.1 1092.36   726.5  1097.1
#Mann= 6, -1 ,  0
       0     0.1       0      90    0.06       0  335.68    0.05       0
   408.1   0.045       0  413.45    0.05       0  430.68     0.1       0
#XS Ineff= 2 , 0
          278.36  983.61
Permanent Ineff=
       F       F
Bank Sta=408.1,413.45
XS Rating Curve= 0 ,0
Exp/Cntr(USF)=0,0
Exp/Cntr=0.3,0.1

Type RM Length L Ch R = 1 ,8506    ,499.6,499.6,499.6
XS GIS Cut Line= 6
1687396.42559984374273.9659890831687313.14098951374319.192276582
1687236.91443592374364.0333942621687175.38503142374407.494921505
1687039.46929276374518.1869573441686891.08277851374623.509581342
#Sta/Elev= 30
       0 1085.46    23.1 1073.59    40.5 1065.88    50.4 1059.05      67 1050.07
    93.6 1040.01   128.6 1019.81   154.9 1003.48   166.6  997.74   176.3  994.36
   181.2  990.92     191  979.78   195.6  976.48   218.5  974.05   232.9  966.91
   298.5  965.32   307.2  963.68   309.9  963.25  313.24963.6802   320.1  965.52
   335.7  966.01   412.3  966.19   424.7  967.86     438  971.56   462.7  983.76
   486.6  998.42   551.2 1029.88     567 1033.72   595.7 1047.02   615.8 1054.42
#Mann= 5, -1 ,  0
       0     0.1       0  193.21    0.06       0  288.54     0.1       0
   307.2   0.045       0  313.24     0.1       0
#XS Ineff= 2 , 0
          250.61  972.63
Permanent Ineff=
       F       F
Bank Sta=307.2,313.24
XS Rating Curve= 0 ,0
Exp/Cntr(USF)=0,0
Exp/Cntr=0.3,0.1

Type RM Length L Ch R = 1 ,8007    ,500.3,500.3,500.3
XS GIS Cut Line= 6
1686979.92151159373887.4569195961686920.66670884373960.400015175
1686813.10097909374082.5910437551686749.35930867374160.133539587
1686705.90729584374222.2400426721686605.43538393 374374.41395092
#Sta/Elev= 30
       0 1116.03      12 1110.75    32.3 1098.61    57.5 1087.72    73.5 1079.07
      94 1072.77    99.5 1070.26   125.2  1053.1   145.5 1044.87   179.1 1026.64
   216.3 1002.22   241.8   988.5   253.2   980.7   258.9  974.98   264.6  963.74
   269.6  959.25     293  958.98  303.85956.4012   308.7  955.74   312.9   956.4
   321.4  958.47   469.4  961.56   490.7   963.6     508  968.93   515.5   972.3
   531.8  982.25   550.9  996.42   560.5 1002.23   574.8 1008.78   615.3 1041.09
#Mann= 5, -1 ,  0
       0     0.1       0  191.63    0.06       0  303.85   0.045       0
   312.9    0.06       0  367.15     0.1       0
Bank Sta=303.85,312.9
XS Rating Curve= 0 ,0
Exp/Cntr(USF)=0,0
Exp/Cntr=0.3,0.1

Type RM Length L Ch R = 1 ,7506    ,500.5,500.5,500.5
XS GIS Cut Line= 6
1686624.94649975373615.9285912511686493.51500408 373741.35255301
1686435.38880801373788.818009257  1686296.491448373895.714777082
1686234.23730743373959.4226549271686182.04351064374201.389965852
#Sta/Elev= 30
       0 1115.55    12.3 1110.56    29.4 1099.08    63.6  1081.1    85.9 1071.28
   111.3 1055.05   148.1 1043.63   193.5 1017.85   209.3 1006.74     230  997.77
   253.2   978.3   256.3     974   261.7  962.06   265.8  956.36   293.2  954.83
   303.4   950.1   307.5  949.48   312.5 950.095   321.8  951.94     381  950.56
   567.3  953.24   583.6  955.19     600  961.18   620.5  972.11   671.1 1005.46
   692.2 1016.64   718.7 1035.46   739.1 1041.45   751.4 1052.11   768.7  1060.5
#Mann= 6, -1 ,  0
       0     0.1       0   241.7    0.06       0   303.4   0.045       0
   312.5    0.06       0  366.79    0.05       0  601.13     0.1       0
Bank Sta=303.4,312.5
XS Rating Curve= 0 ,0
Exp/Cntr(USF)=0,0
Exp/Cntr=0.3,0.1

Type RM Length L Ch R = 1 ,7006    ,537.3,537.3,537.3
XS GIS Cut Line= 6
1686473.83230068373351.6030044261686383.18976542 373376.09606567
1686298.35069625373397.8256810011686225.29244342373414.851237506
1685968.48324576373469.2120211721685876.76558143373488.627008587
#Sta/Elev= 30
       0  1085.4     5.9 1081.92    26.6  1073.4      38 1064.67    51.1  1059.9
    63.9 1050.66    72.2 1047.71    88.8 1044.12    97.1 1040.98   134.2 1022.61
   146.6 1015.01   162.5 1009.91   179.7  999.79   216.6  985.72   225.6  980.78
   241.3  969.91   249.5  960.49   262.3  951.18     270  949.67   290.4  949.44
  301.28943.6398   306.8  942.69  313.27 943.624     319  945.93     323   946.4
   466.2  945.15   545.7  948.72   564.3  950.17   588.9  954.07   612.7  964.32
#Mann= 7, -1 ,  0
       0     0.1       0  231.47    0.06       0  301.28   0.045       0
  313.27    0.06       0  336.49    0.05       0  376.49     0.1       0
  431.49    0.05       0
Bank Sta=301.28,313.27
XS Rating Curve= 0 ,0
Exp/Cntr(USF)=0,0
Exp/Cntr=0.3,0.1

Type RM Length L Ch R = 1 ,6468    ,468.6,468.6,468.6
XS GIS Cut Line= 6
1686020.84975495372629.8314028061685972.85200343372807.089657754
1685995.96678659372968.0197820961685963.43765217373070.313868836
1685907.95515159373154.4357478321685813.38939583373346.519353166
#Sta/Elev= 30
       0 1009.06    56.7  977.74    73.3  967.88    85.7  958.51    89.8   957.4
   103.9  956.97   118.8  953.45   139.6  950.92   185.1  949.66   201.2  948.26
   213.3  949.46   269.6  949.66   346.4  948.58   384.7  945.54   397.3  940.89
  413.72 939.358   418.3  938.97  420.02939.3505   426.7  941.33     435     942
   537.8  942.64   597.4  941.72   665.6  944.45   676.2  946.89   686.7  951.16
   700.4  954.68     718  960.72     744  966.28   757.6  971.71   768.6  972.98
#Mann= 7, -1 ,  0
       0     0.1       0      30    0.06       0  233.64     0.1       0
  413.72   0.045       0  420.02     0.1       0   543.7    0.05       0
  671.49     0.1       0
Bank Sta=413.72,420.02
XS Rating Curve= 0 ,0
Exp/Cntr(USF)=0,0
Exp/Cntr=0.3,0.1

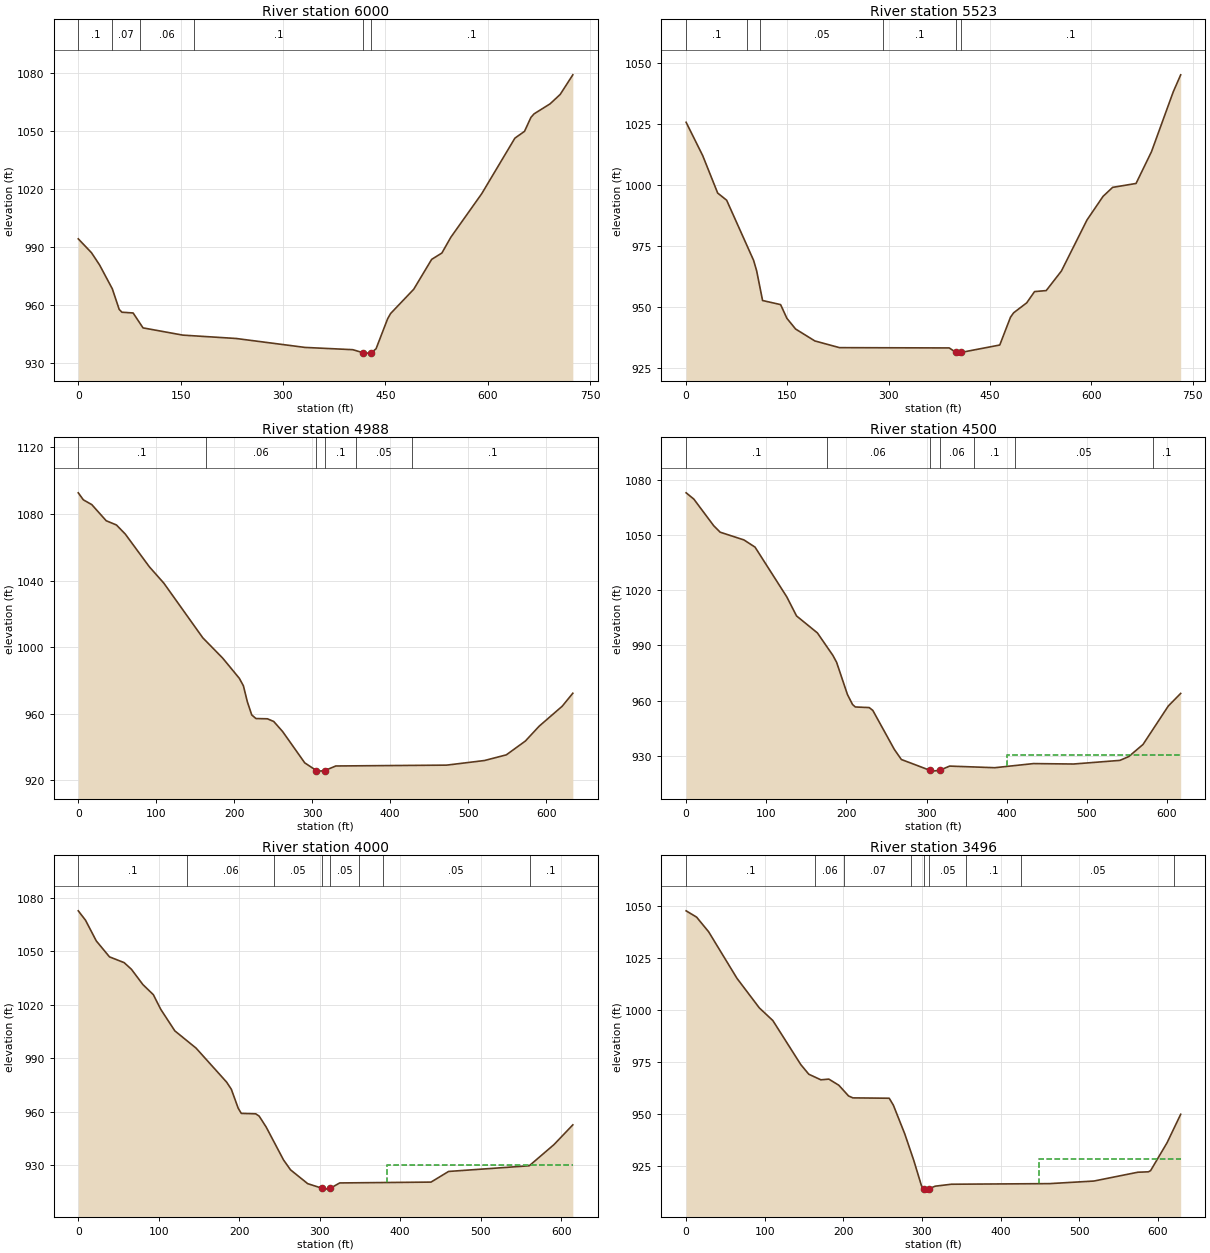
Type RM Length L Ch R = 1 ,6000    ,477,477,477
XS GIS Cut Line= 6
1685904.01493339 372609.944504091685800.96652043372778.313140512
1685732.08247185372842.3179337531685496.96712843372927.320388421
1685416.98566109372964.0414435861685335.92808042373014.321854845
#Sta/Elev= 30
       0  994.17    19.3  987.03    31.2  980.69    49.9  968.34      60  957.69
      64  956.24    80.4  955.85    94.9  948.15   153.1  944.41   231.3  942.67
   332.3  938.05   402.3  936.88   417.7  935.27   423.6   935.1   429.3  935.27
   436.4  937.33   453.4  952.86   457.7  955.55   491.6   968.1   517.9  983.55
   532.9  986.84     546  994.98   591.3 1017.51   639.9 1046.21     654 1049.73
   663.4 1056.93   668.1 1058.79   691.5 1063.95   706.3 1068.82   724.8 1078.94
#Mann= 6, -1 ,  0
       0     0.1       0      50    0.07       0      90    0.06       0
     170     0.1       0   417.7   0.045       0   429.3     0.1       0
Bank Sta=417.7,429.3
XS Rating Curve= 0 ,0
Exp/Cntr(USF)=0,0
Exp/Cntr=0.3,0.1

Type RM Length L Ch R = 1 ,5523    ,534.9,534.9,534.9
XS GIS Cut Line= 6
1685734.15768871372407.8845030921685586.30159542372478.983686671
1685390.37515001372504.6877035051685305.51049034372568.022550583
1685251.05259401372624.7028834221685110.99316284372747.015302837
#Sta/Elev= 30
       0 1025.64    24.5 1011.99    46.7  996.61      60  993.66    99.9  968.99
   104.4  964.71   113.2   952.5   139.9  950.82   149.2  945.19   162.1   940.8
   190.6  935.91   227.1  933.16   389.6  933.04   399.5  931.22   403.3  930.91
  407.67931.2248   464.4  934.24   480.3  945.65     485  947.48   504.3  951.55
   515.9  956.16   533.2  956.58   555.7  964.62   593.5  985.52   617.3  995.23
   631.5  998.93   666.2 1000.54   689.1  1013.6   721.2 1038.08   732.3 1045.12
#Mann= 6, -1 ,  0
       0     0.1       0      90    0.06       0     110    0.05       0
  291.44     0.1       0   399.5   0.045       0  407.67     0.1       0
Bank Sta=399.5,407.67
XS Rating Curve= 0 ,0
Exp/Cntr(USF)=0,0
Exp/Cntr=0.3,0.1

Type RM Length L Ch R = 1 ,4988    ,487.9,487.9,487.9
XS GIS Cut Line= 6
1685467.40517968 371998.693636761685302.88024625372195.293637261
1685224.11301534372259.9450827541685155.09412451372303.184825674
1685078.32656151372356.0065704291684988.90055926372403.783049673
#Sta/Elev= 30
       0 1092.67     6.5 1088.48    17.4 1085.57    35.8 1075.92      49 1073.35
    60.3 1067.91    91.2 1048.24   109.8 1038.41   159.7 1005.63   185.3  993.39
   206.6  981.28   211.8   976.8   216.9  967.15   222.5  959.31   227.9  957.14
   242.6  956.99   250.7  955.38   262.1  949.34   290.5  930.52  305.53925.8955
   308.8  925.57   316.1  925.89   330.3  928.66   472.5  929.17     521  931.94
     549  935.34   573.4  943.62   591.1  952.54   620.7  964.55   634.3  972.34
#Mann= 6, -1 ,  0
       0     0.1       0  163.82    0.06       0  305.53   0.045       0
   316.1     0.1       0  356.38    0.05       0  428.28     0.1       0
Bank Sta=305.53,316.1
XS Rating Curve= 0 ,0
Exp/Cntr(USF)=0,0
Exp/Cntr=0.3,0.1

Type RM Length L Ch R = 1 ,4500    ,500,500,500
XS GIS Cut Line= 6
1685182.52221926371766.9001370821685031.36176042 371871.97604242
1684964.32022785371907.1173763421684871.22297309371943.625833511
1684802.74673209371974.4164543451684644.17880775372064.294883505
#Sta/Elev= 30
       0 1073.05     9.6 1069.65    34.4 1055.16    42.5 1051.62    72.1 1047.43
      86  1043.5   125.6 1016.45   137.8 1006.05   163.8  996.83   183.2  984.55
   187.8  980.81   201.3  963.31   207.7  957.85   211.2  956.51   228.5  956.18
     233  954.63   259.8  933.45   268.6  927.93   304.3  922.03   307.3   921.6
  316.36922.0257   328.8  924.34   385.2  923.46   433.4   925.7   483.5  925.47
   541.4  927.45   552.4  929.52   570.2  936.12   601.8  957.07   617.2  963.89
#Mann= 7, -1 ,  0
       0     0.1       0  175.18    0.06       0   304.3   0.045       0
  316.36    0.06       0  359.82     0.1       0  409.82    0.05       0
  582.87     0.1       0
#XS Ineff= 2 , 0
                          400.58          930.18
Permanent Ineff=
       F       F
Bank Sta=304.3,316.36
XS Rating Curve= 0 ,0
Exp/Cntr(USF)=0,0
Exp/Cntr=0.3,0.1

Type RM Length L Ch R = 1 ,4000    ,504.3,504.3,504.3
XS GIS Cut Line= 6
1684892.22030643371415.4208531681684806.93570009371457.303971499
  1684726.502462371493.5571798381684657.16106525371522.381925344
 1684565.4771935371562.3080265821684330.53835893371664.620157927
#Sta/Elev= 30
       0 1072.55       9  1067.3    22.4 1055.67    38.8 1046.74      57  1043.5
    66.1 1039.75    80.3  1031.2    93.3 1025.53   102.5 1017.33     120 1005.24
   146.4  995.56   184.3  976.53   190.2  972.51   198.8  961.82   202.6  958.96
   220.5  958.72   224.8  957.44   233.5  951.31   255.1  932.85   263.8   927.3
   285.1  919.56   303.1  916.96   307.5  916.49  313.14916.9531   324.9  919.96
   438.4  920.43   460.2   926.4   560.5  929.59   591.1  941.42   614.6  952.53
#Mann= 8, -1 ,  0
       0     0.1       0  135.01    0.06       0  243.24    0.05       0
   303.1   0.045       0  313.14    0.05       0  348.33    0.08       0
  378.33    0.05       0  560.83     0.1       0
#XS Ineff= 2 , 0
                          383.97          929.82
Permanent Ineff=
       F       F
Bank Sta=303.1,313.14
XS Rating Curve= 0 ,0
Exp/Cntr(USF)=0,0
Exp/Cntr=0.3,0.1

Type RM Length L Ch R = 1 ,3496    ,226.3,226.3,226.3
XS GIS Cut Line= 6
  1684604.609005370854.0906110111684445.67854859371055.100051507
1684376.99594317371128.2235929221684317.13385817371183.327485338
1684248.36168601371246.2810995881684175.80015133371312.146781504
#Sta/Elev= 30
       0 1047.46    13.3 1044.44    28.6 1037.42    64.7 1015.04    93.2 1000.81
   110.3  994.78   145.9  973.61   156.1  968.98   171.4  966.31   181.6  966.64
   194.3  963.69   206.7  958.54   212.2  957.63   258.4  957.46   263.7  954.09
   278.2  940.29   289.5  927.75   299.4  915.45  302.37914.0914   305.3  913.81
   309.3  914.09     317  915.23   337.6  916.16   462.2  916.45   518.8  917.69
   574.7  921.93   588.1  922.12   590.9  922.68   611.9  936.11   629.2  949.75
#Mann= 9, -1 ,  0
       0     0.1       0  163.75    0.06       0  201.25    0.07       0
  286.25    0.05       0  302.37   0.045       0   309.3    0.05       0
  356.25     0.1       0  426.57    0.05       0  621.17     0.1       0
#XS Ineff= 2 , 0
                          448.89           928.4
Permanent Ineff=
       F       F
Bank Sta=302.37,309.3
XS Rating Curve= 0 ,0
Exp/Cntr(USF)=0,0
Exp/Cntr=0.3,0.1

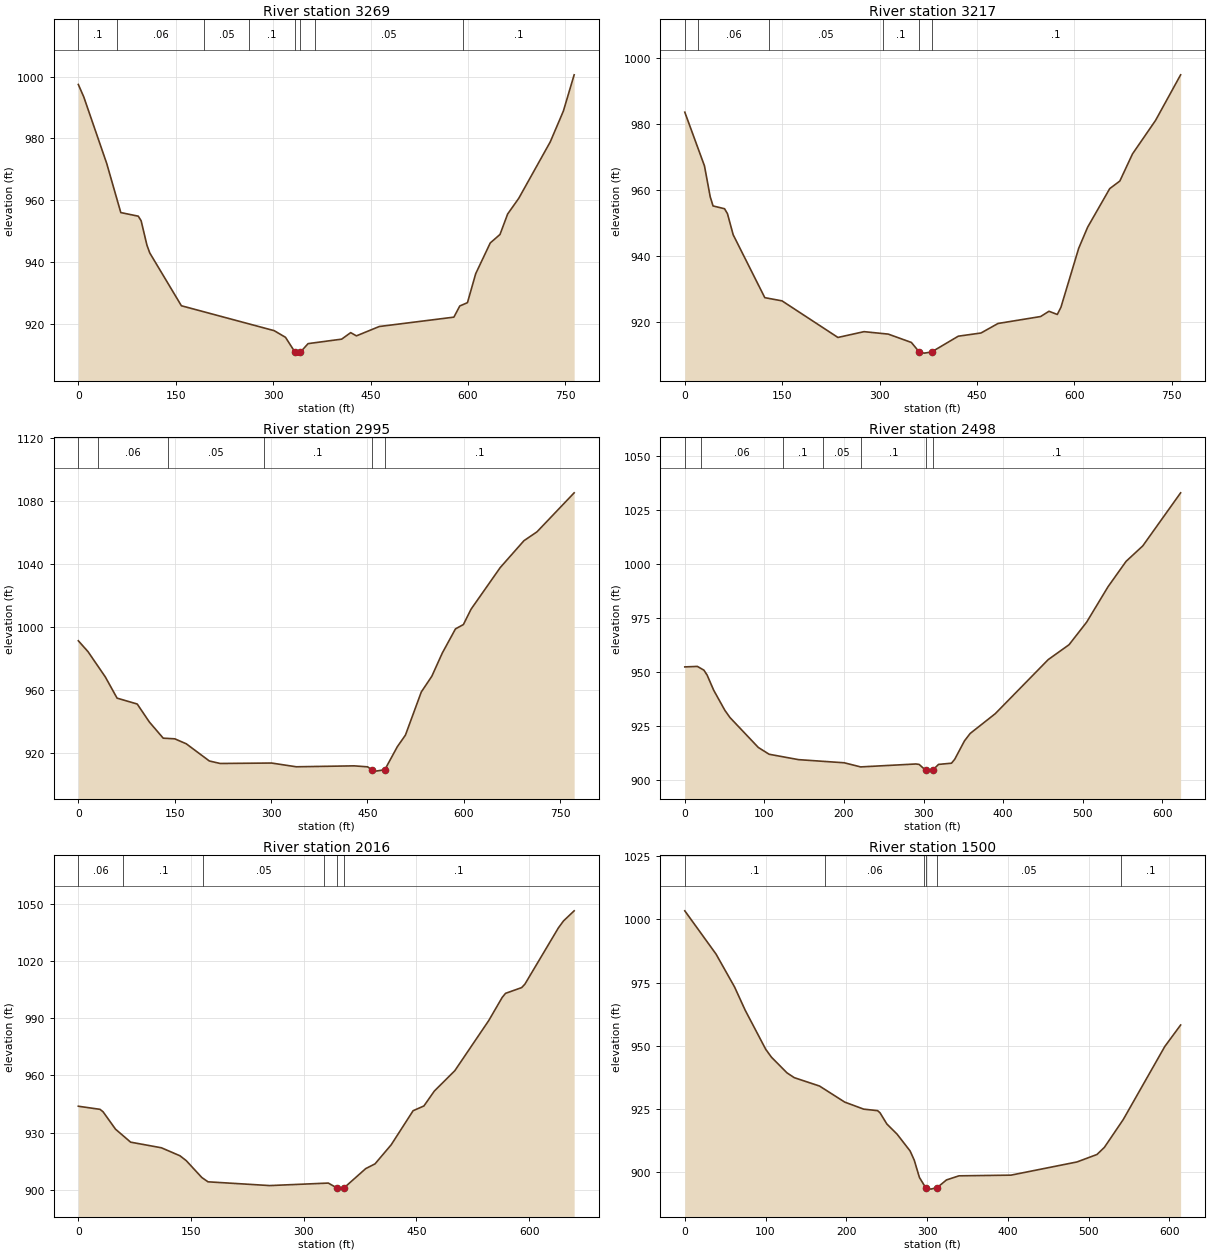
Type RM Length L Ch R = 1 ,3269    ,52,52,52
XS GIS Cut Line= 5
1684435.58524145370716.8798335491684288.00825948370786.568963925
1684271.61081704370887.0032988791684180.38125199371095.617776249
1683925.48876064371187.117644938
#Sta/Elev= 30
       0  997.44     8.4  993.41    43.7  971.92    65.4  956.04    92.3  954.88
    96.7   953.4   105.6  945.54     110     943   158.7  925.93   301.6  917.88
     319  915.73   333.6  910.95   336.5  910.62  341.96910.9493   353.8  913.69
   405.5  915.14   419.4  917.24   428.2   916.2   463.4  919.22   578.3  922.25
   587.4  925.86   599.2  926.93   611.9  936.29   634.3  946.22   649.3  948.97
   661.1  955.59   678.1  960.62   726.7  978.89   746.9  988.85   763.5 1000.56
#Mann= 8, -1 ,  0
       0     0.1       0      60    0.06       0   193.2    0.05       0
   263.2     0.1       0   333.6   0.045       0  341.96     0.1       0
  364.97    0.05       0  592.66     0.1       0
Bank Sta=333.6,341.96
XS Rating Curve= 0 ,0
Exp/Cntr(USF)=0,0
Exp/Cntr=0.3,0.1

Type RM Length L Ch R = 1 ,3217    ,222.3,222.3,222.3
XS GIS Cut Line= 5
1684399.48311541370675.3205648731684251.90613344370745.009695249
1684235.50869099370845.4440302031684144.27912594371054.058507573
 1683889.3866346371145.558376263
#Sta/Elev= 30
       0  983.61    30.3   967.3    39.1  957.96    43.5  955.14    61.2  954.29
    65.7  952.79    74.5  946.39   123.2  927.29   149.7  926.32   235.8  915.21
     276  916.97   313.4  916.22   348.9  913.69     361   910.8   368.8  910.45
  379.93910.7858   421.1  915.59   456.1  916.56   482.3  919.45   547.9  921.56
   560.8  923.16   573.6  922.19   579.2  924.37   606.5  942.26   620.3  948.68
   654.3  960.39   669.9   962.7   689.4  970.94   724.9  981.11   763.5  994.95
#Mann= 6, -1 ,  0
       0     0.1       0      20    0.06       0     130    0.05       0
  304.97     0.1       0     361   0.045       0  379.93     0.1       0
Bank Sta=361,379.93
XS Rating Curve= 0 ,0
Exp/Cntr(USF)=0,0
Exp/Cntr=0.3,0.1

Type RM Length L Ch R = 1 ,2995    ,497,497,497
XS GIS Cut Line= 6
1684405.88014888370633.7596965061684219.74527343370728.393027753
1684137.12732843370804.3800805061684070.10548083370869.585002586
1683974.04399318370900.3661089991683723.68327342370954.987390846
#Sta/Elev= 30
       0  991.15      15  984.28    42.1  968.11    60.3   954.7    91.7  950.95
   110.5  939.55   132.1  929.26   150.1  928.84     168  925.68   203.9  914.76
   220.8  913.17   300.7  913.45   339.2  911.07   429.3  911.66   450.3  911.03
   456.7  909.19   462.9  908.31  477.01909.1893   496.5  923.84   509.1   931.2
   533.8  958.63   550.2  968.63   566.5  983.38     587  998.72   599.3 1001.45
   611.3 1011.26   656.6 1037.66   693.5 1054.73   713.9 1060.41   771.7 1085.18
#Mann= 6, -1 ,  0
       0     0.1       0      30    0.06       0     140    0.05       0
  288.81     0.1       0   456.7   0.045       0  477.01     0.1       0
Bank Sta=456.7,477.01
XS Rating Curve= 0 ,0
Exp/Cntr(USF)=0,0
Exp/Cntr=0.3,0.1

Type RM Length L Ch R = 1 ,2498    ,482.6,482.6,482.6
XS GIS Cut Line= 6
1684199.48842417370349.3609774261683949.61064309370406.151874334
1683850.94089292370424.8421256691683778.47056542370454.945411921
 1683696.9474345370495.7766950881683611.70711942370541.432443678
#Sta/Elev= 30
       0  952.51    15.8  952.74      24  951.01    28.1   948.7    36.3  941.72
    50.4  932.37    56.8  929.05    92.4   915.2     106  912.06   142.9  909.57
   200.4  908.11   220.9   906.2   290.4  907.56   294.4  907.36   302.6   904.7
   306.6  904.25   311.4904.6672   318.8  907.36   335.1  907.92   339.2  909.76
   351.4  918.25   358.6   921.7   390.1  930.85   456.6  955.88   482.8  962.78
   504.9  973.22   531.8  989.64   554.5  1001.4   575.4 1008.53     623 1033.12
#Mann= 7, -1 ,  0
       0     0.1       0      20    0.06       0  123.75     0.1       0
  173.75    0.05       0  221.25     0.1       0   302.6   0.045       0
   311.4     0.1       0
Bank Sta=302.6,311.4
XS Rating Curve= 0 ,0
Exp/Cntr(USF)=0,0
Exp/Cntr=0.3,0.1

Type RM Length L Ch R = 1 ,2016    ,515.8,515.8,515.8
XS GIS Cut Line= 6
1684044.47462659370050.2746333331683755.13137326369986.625810504
1683652.58892742370014.1848105041683588.81936993370053.661437586
1683511.08888234370094.2066320931683422.80887517 370128.05400534
#Sta/Elev= 30
       0  943.84    28.9  942.21      33  940.89    49.5  931.81    69.6  925.02
   110.5  922.08   135.3  917.88   143.6  915.34   164.4  906.48   172.6  904.25
   254.7  902.28   332.7  903.59   344.2  901.02   349.4  900.42   353.4  901.02
   382.4  911.16   394.8  913.65   416.3  923.63   445.5  941.49   459.9  943.99
   473.7  951.77     501  962.46   546.1  988.69   564.1 1000.87   568.5 1002.97
   589.9 1005.97   594.2 1007.75   638.8 1037.24   645.6 1040.89   659.8 1046.19
#Mann= 6, -1 ,  0
       0    0.06       0      60     0.1       0  166.07    0.05       0
  326.44     0.1       0   344.2   0.045       0   353.4     0.1       0
Bank Sta=344.2,353.4
XS Rating Curve= 0 ,0
Exp/Cntr(USF)=0,0
Exp/Cntr=0.3,0.1

Type RM Length L Ch R = 1 ,1500    ,614.8,614.8,614.8
XS GIS Cut Line= 6
1683929.94368768369405.8353054231683854.03439067369460.905733332
1683637.40391843369609.1541244981683572.02379984369646.652409092
1683496.01115659369690.9849975851683415.39648843 369739.76377143
#Sta/Elev= 30
       0 1003.38    38.7  986.26    61.6  973.27    74.8  964.05   100.2  948.61
   107.3  945.48   126.5  939.29   135.5  937.39   166.8  934.07     198  927.72
   221.5  924.93   238.7  924.33   241.7  923.49   250.2  919.05   262.8  915.05
     279  908.37   284.1  904.74   290.5  897.91  298.16893.9097   304.6  893.29
   312.5   893.9     324  896.93   339.5  898.55   403.9  898.82   485.6  904.04
   510.3  906.99   519.5   909.8   542.9  920.84   594.3  949.71   613.9  958.21
#Mann= 6, -1 ,  0
       0     0.1       0  173.78    0.06       0  296.28    0.05       0
  298.16   0.045       0   312.5    0.05       0  539.65     0.1       0
Bank Sta=298.16,312.5
XS Rating Curve= 0 ,0
Exp/Cntr(USF)=0,0
Exp/Cntr=0.3,0.1

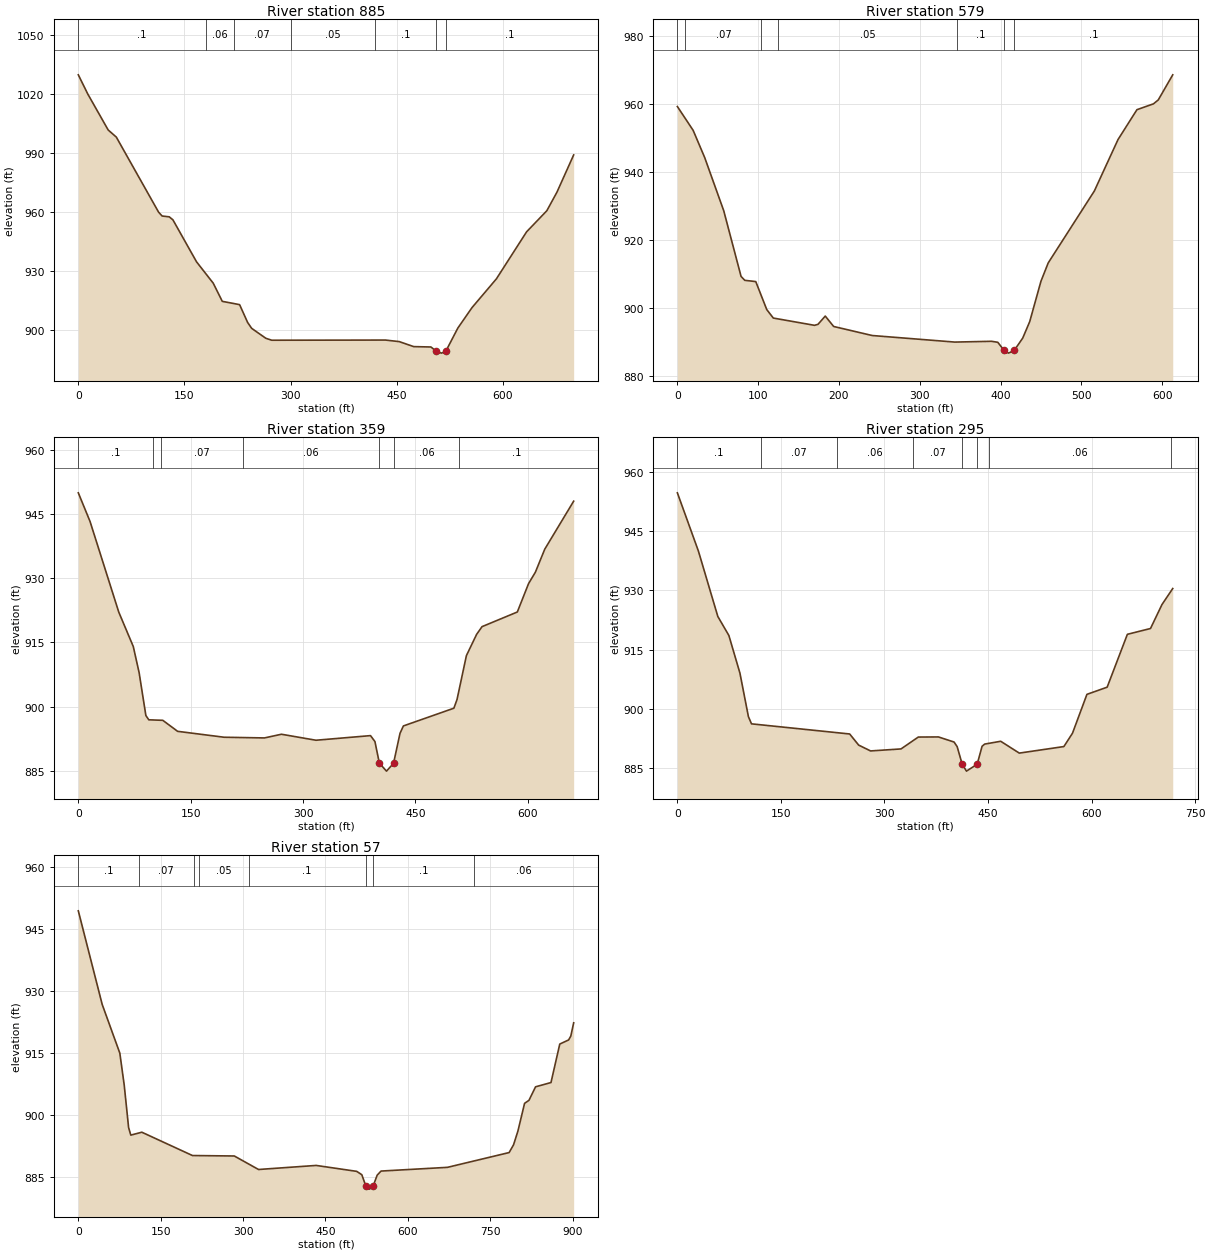
Type RM Length L Ch R = 1 ,885     ,305.7,305.7,305.7
XS GIS Cut Line= 2
1683634.94262765368980.2527601131683074.61127422369400.127720948
#Sta/Elev= 30
       0  1029.9    13.5 1020.08    42.2 1001.87    53.7  998.26   113.5  960.08
   118.5  958.12   128.5  957.71   133.7   956.2   167.2   934.8   190.8  923.94
   203.5  914.74     228  913.07   239.4  903.97   245.1  901.01   265.1  895.96
   273.4  894.98   434.1  895.06   453.7  894.27   474.1  891.73   498.4  891.54
  506.31889.3102   513.4  888.42   519.4  889.32   536.5  901.16   556.5  911.55
     591  926.18   633.7   950.1   662.3  960.82   676.6  970.26   700.2  989.17
#Mann= 7, -1 ,  0
       0     0.1       0     180    0.06       0     220    0.07       0
     300    0.05       0     420     0.1       0  506.31   0.045       0
   519.4     0.1       0
Bank Sta=506.31,519.4
XS Rating Curve= 0 ,0
Exp/Cntr(USF)=0,0
Exp/Cntr=0.3,0.1

Type RM Length L Ch R = 1 ,579     ,220.5,220.5,220.5
XS GIS Cut Line= 6
1683401.20805444368863.7494290811683241.44328212368949.869335581
1683174.41126395368983.5589007481683016.41912586369058.816624244
1682938.80018661369099.3122781711682857.67830161369146.609755744
#Sta/Elev= 30
       0  959.18    19.5  952.18    33.8  944.17    57.4   928.5    78.8  909.21
    83.4  908.05      97  907.68   110.6  899.45   118.7  896.95   169.7  894.81
     174   895.1     183  897.53   193.4  894.47   241.1  891.81   343.3  889.88
   388.8  890.11   396.5  889.82  404.34887.4188   409.7  886.63   416.8  887.41
   427.4  891.07     436  895.89   449.9  907.76   458.9  913.17     516  934.33
   545.3  949.47   568.7  958.25   589.2  959.98   595.1  961.13     613  968.51
#Mann= 7, -1 ,  0
       0     0.1       0      10    0.07       0  103.92    0.08       0
  123.92    0.05       0  346.53     0.1       0  404.34   0.045       0
   416.8     0.1       0
Bank Sta=404.34,416.8
XS Rating Curve= 0 ,0
Exp/Cntr(USF)=0,0
Exp/Cntr=0.3,0.1

Type RM Length L Ch R = 1 ,359     ,64,64,64
XS GIS Cut Line= 3
1683291.89904685368669.2081026241682850.73896567368902.140625487
 1682803.0936769369057.428974063
#Sta/Elev= 30
       0  949.94    15.7  943.24      54   922.1    73.4  914.06    81.2  907.95
    90.2  897.95    94.1  896.95   112.8  896.83   132.6  894.26   194.7  892.88
   248.5  892.72   271.2  893.58   317.3  892.18   390.1  893.26     396  891.87
   401.9  886.84   411.4  884.97   420.8886.7783   429.5   893.8     434  895.52
   501.4  899.66   505.6  901.69   518.1  911.93   531.7  916.88     539   918.7
   586.1  922.12   601.1  928.75   610.2  931.41   622.7  936.78   661.3  947.99
#Mann= 7, -1 ,  0
       0     0.1       0     100    0.06       0     110    0.07       0
     220    0.06       0   401.9   0.045       0   420.8    0.06       0
  508.88     0.1       0
Bank Sta=401.9,420.8
XS Rating Curve= 0 ,0
Exp/Cntr(USF)=0,0
Exp/Cntr=0.3,0.1

Type RM Length L Ch R = 1 ,295     ,237.4,237.4,237.4
XS GIS Cut Line= 4
1683310.59479383368644.2610749331683210.01029532368649.554995907
1682807.26684552368860.0446343121682759.62155675369015.332982887
#Sta/Elev= 30
       0  954.76    30.5  939.97    58.6   923.4    74.6  918.58    90.6  909.05
   102.9     898   107.4  896.17   249.6   893.6   262.6  890.78   279.9   889.3
     324  889.81     349  892.82   378.2  892.85   400.8  891.56   405.3  890.39
   412.6  885.93   418.8  884.18   434.3885.9268   441.4  890.48   445.2  891.04
   468.4  891.75   495.3  888.75   559.9  890.41   572.4   893.8   593.3  903.65
   622.6  905.47   651.9  918.88   685.4  920.35     702  926.42   717.6  930.49
#Mann= 8, -1 ,  0
       0     0.1       0  120.72    0.07       0  230.72    0.06       0
  340.72    0.07       0   412.6   0.045       0   434.3    0.07       0
  450.72    0.06       0  715.16     0.1       0
Bank Sta=412.6,434.3
XS Rating Curve= 0 ,0
Exp/Cntr(USF)=0,0
Exp/Cntr=0.3,0.1

Type RM Length L Ch R = 1 ,57      ,,,
XS GIS Cut Line= 4
1683307.53188817368629.3256444261682816.68162257368595.705763221
1682776.33776512368662.9455256321682752.13145065368993.765156696
#Sta/Elev= 30
       0  949.31    43.5  926.71    75.6  914.96    83.6  907.25    91.6  896.98
    95.6  895.16   115.7  895.86   207.9  890.23   284.1  890.12   328.2  886.86
   433.2  887.84     507  886.41   516.3   885.6  523.82882.8102   530.3  882.12
   536.8  882.82   544.3   885.5   551.3  886.48   672.3  887.38   784.6  890.95
   792.6  892.81   800.6  896.15   812.7  902.83   820.7  903.56   832.7  906.82
   860.8  907.85   876.8  917.14   892.9  918.14   896.9  919.07   902.1  922.27
#Mann= 8, -1 ,  0
       0     0.1       0     110    0.07       0     210    0.06       0
     220    0.05       0     310     0.1       0  523.82   0.045       0
   536.8     0.1       0  720.41    0.06       0
Bank Sta=523.82,536.8
XS Rating Curve= 0 ,0
Exp/Cntr(USF)=0,0
Exp/Cntr=0.3,0.1
LCMann Table=0

Chan Stop Cuts=-1
Use User Specified Reach Order=0
Composite Channel Slope=5